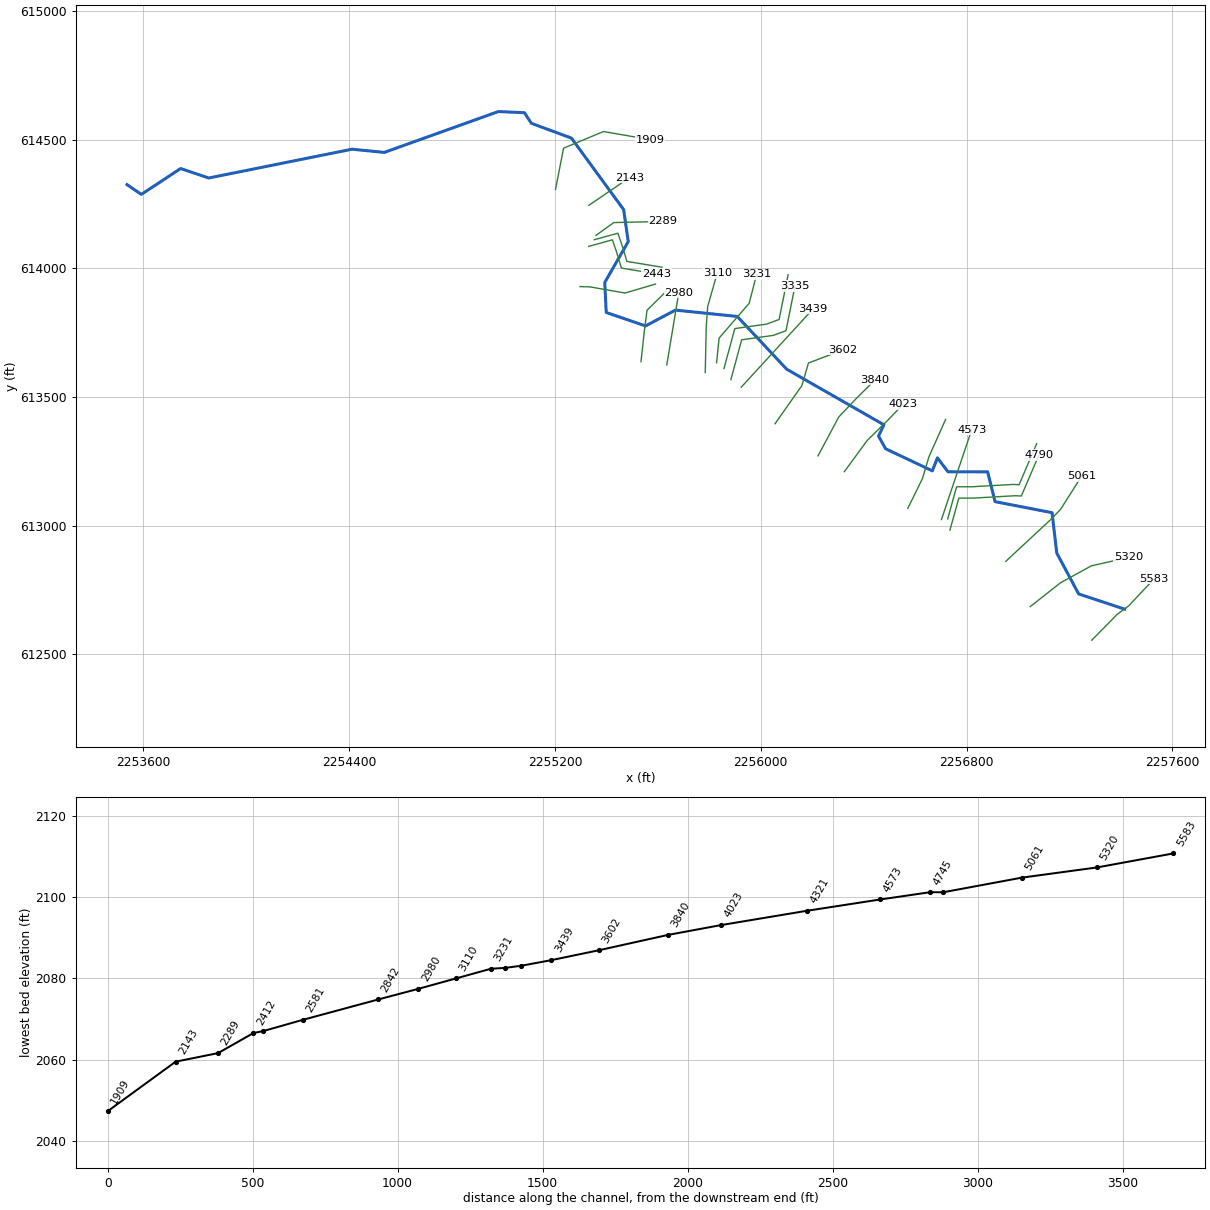
--- TYGVRV2T2.prj (project) ---

Proj Title=TYGVRV2T2
Current Plan=p01
Default Exp/Contr=0,0
English Units
Geom File=g01
Flow File=f01
Plan File=p01
BEGIN DESCRIPTION:
----------MODEL BY WOOD PLC 2022----------
AFH study
Randolph County, WV
HEC-RAS Version: RAS 6.2
Vertical Datum: NAVD88
Projection: NAD 1983 StatePlane West Virginia S FIPS 4702 (US Feet)
Terrain: 1-meter LIDAR (FEMA Region III 3DEP collected 2016-2018)
Land Use: 2019 NLCD
Hydrologic Method:
WV SIR2010-5033 regression equations
Additional Model Notes:
Main stem backwater dominates DS of XS 1909
END DESCRIPTION:
DSS Export Rating Curves= 0
DSS Export Rating Curve Sorted= 0
DSS Export Volume Flow Curves= 0
DXF OffsetX= 0
DXF OffsetY= 0
DXF ScaleX= 0
DXF ScaleY= 0

--- TYGVRV2T2.p01 (plan) ---

Plan Title=Floodplain
Program Version=6.20
Short Identifier=Floodplain
Geom File=g01
Flow File=f01
Subcritical Flow
K Sum by GR= 0
Std Step Tol= 0.01
Critical Tol= 0.01
Num of Std Step Trials= 20
Max Error Tol= 0.3
Flow Tol Ratio= 0.001
Split Flow NTrial= 30
Split Flow Tol= 0.02
Split Flow Ratio= 0.02
Log Output Level= 0
Friction Slope Method= 1
Unsteady Friction Slope Method= 2
Unsteady Bridges Friction Slope Method= 1
Parabolic Critical Depth
Global Vel Dist= 0 , 0 , 0
Global Log Level= 0
CheckData=True
Encroach Param=-1 ,0,0, 0
Mapping Interval=1HOUR
Computation Time Step Use Courant=        0
Computation Time Step Use Time Series=    0
Computation Time Step Count To Double=0
Computation Time Step Max Doubling=0
Computation Time Step Max Halving=0
Computation Time Step Residence Courant=0
Run HTab= 0
Run UNet= 0
Run Sediment= 0
Run PostProcess= 0
Run WQNet= 0
Run RASMapper=-1
UNET Theta= 0
UNET Theta Warmup= 0
UNET ZTol= 0
UNET ZSATol= 0
UNET MxIter= 0
UNET Max Iter WO Improvement= 0
UNET MaxInSteps= 0
UNET DtIC= 0
UNET DtMin= 0
UNET MaxCRTS= 0
UNET WFStab= 0
UNET SFStab= 0
UNET WFX= 1
UNET SFX= 1
UNET Gravity=32.174
UNET 1D Methodology=Finite Difference
UNET DSS MLevel= 1
UNET Pardiso=0
UNET DZMax Abort= 0
UNET Use Existing IB Tables= 0
UNET Froude Reduction=False
UNET Froude Limit= 0
UNET Froude Power= 0
UNET D1 Cores= 0
UNET WindReference=Eulerian
UNET WindDragFormulation=Hsu (1988)
UNET D2 Coriolis=0
UNET D2 Cores= 0
UNET D2 Theta= 1
UNET D2 Theta Warmup= 1
UNET D2 Z Tol= 0.01
UNET D2 Volume Tol= 0.01
UNET D2 Max Iterations= 20
UNET D2 Equation= 0
UNET D2 RampUpFraction=0.1
UNET D2 TimeSlices= 1
UNET D2 Turbulence Formulation=Non-Conservative (original)
UNET D2 Eddy Viscosity=0.3
UNET D2 Transverse Eddy Viscosity=0.1
UNET D2 Smagorinsky Mixing=0
UNET D2 BCVolumeCheck=0
UNET D2 Cores=0
UNET D2 SolverType=PARDISO (Direct)
UNET D2 Minimum Iterations= 2147483647
UNET D2 Maximum Iterations= 2147483647
UNET D2 Restart Number= 10
UNET D2 Relaxation Coeff=1.3
UNET D2 SOR Precondition Iterations= 10
UNET D2 ILUT Maximum Fill= 8
UNET D2 ILUT Tolerance=1E-08
UNET D1D2 MaxIter= 0
UNET D1D2 ZTol=0.01
UNET D1D2 QTol=0.1
UNET D1D2 MinQTol=1
Write IC File= 0
Write IC File at Fixed DateTime=0
Write IC File at Sim End=0
Echo Input=False
Echo Parameters=False
Echo Output=False
Write Detailed= 0
HDF Write Warmup=0
HDF Write Time Slices=0
HDF Flush=0
HDF Compression= 1
HDF Chunk Size= 1
HDF Spatial Parts= 1
HDF Use Max Rows=0
HDF Fixed Rows= 1
Calibration Method= 0
Calibration Iterations= 20
Calibration Max Change=0.05
Calibration Tolerance=0.2
Calibration Maximum=1.5
Calibration Minimum=0.5
Calibration Optimization Method= 1
WQ AD Non Conservative
WQ ULTIMATE=-1
WQ Max Comp Step=1HOUR
WQ Output Interval=15MIN
WQ Output Selected Increments= 0
WQ Output face flow=0
WQ Output face velocity=0
WQ Output face area=0
WQ Output face dispersion=0
WQ Output cell volume=0
WQ Output cell surface area=0
WQ Output cell continuity=0
WQ Output cumulative cell continuity=0
WQ Output face conc=0
WQ Output face dconc_dx=0
WQ Output face courant=0
WQ Output face peclet=0
WQ Output face adv mass=0
WQ Output face disp mass=0
WQ Output cell mass=0
WQ Output cell source sink temp=0
WQ Output nsm pathways=0
WQ Output nsm derived pathways=0
WQ Create Restart=0
WQ Fixed Restart=0
WQ System Summary=0
WQ Write To DSS=0
Sorting and Armoring Iterations= 10
XS Update Threshold= 0.02
Bed Roughness Predictor= 0
Hydraulics Update Threshold= 0.02
Energy Slope Method= 1
Volume Change Method= 1
Sediment Retention Method= 0
Sediment TS Multiplier= 1
Warm Up Method= 0
XS Weighting Method= 0
Number of US Weighted Cross Sections= 1
Number of DS Weighted Cross Sections= 1
Upstream XS Weight=0
Main XS Weight=1
Downstream XS Weight=0
Number of DS XS's Weighted with US Boundary= 1
Upstream Boundary Weight= 1
Weight of XSs Associated with US Boundary= 0
Number of US XS's Weighted with DS Boundary= 1
Downstream Boundary Weight= 0.5
Weight of XSs Associated with DS Boundary= 0.5
Percentile Method= 0
Sediment Output Level= 3
Mass or Volume Output= 0
Output Increment Type= 1
Profile and TS Output Increment= 1
Transport Output Increment 1
XS Output Flag= 0
XS Output Increment= 10
Read HDF5 Sediment Hotstart= 0
Sediment Hotstart Type= 0
Write Gradation File= 0
Read Gradation Hotstart= 0
Write HDF5 File= 1
Write Binary Output= 1
Write DSS Sediment File= 0
DSS Sediment Output Type= 1
SV Curve= 0
Specific Gage Flag= 0
Subcell Erosion Methods= 0
Subcell Deposition Methods= 0
Advection Scheme= 1
Matrix Solver= 0
Implicit Weighting Factor= 1
Maximum Outer Loop Convergence Iterations= 5
Convergence Maximum Absolute= 0.001
Convergence RMSE= 0.0001
Grain Fractions Max Abs Error= 0.001
Max Subgrid Regions= 1
Max Subgrid Length Scale= 3.402823E+38
Initial Layer Thickness= 3.402823E+38
Min Layer Thickness= 3.402823E+38
Max Layer Thickness= 3.402823E+38
Number of Layers= 5

--- TYGVRV2T2.f01 (steady flow) ---

Flow Title=Flow
Program Version=6.20
Number of Profiles= 1
Profile Names=P100yr
River Rch & RM=TYGVRV2T2,Main,5583
     145
River Rch & RM=TYGVRV2T2,Main,3602
     184
Boundary for River Rch & Prof#=TYGVRV2T2,Main            , 1
Up Type= 0
Dn Type= 3
Dn Slope=0.05174
DSS Import GetInterval= 0
DSS Import GetPeak= 0
DSS Import FillOption= 0

--- TYGVRV2T2.g01 (geometry) ---

Geom Title=Geometry
Program Version=6.20

River Reach=TYGVRV2T2       ,Main
Reach XY= 30
2257414.32539341612675.2236372232257235.53900002612734.405000001
2257150.57914804612893.150529876 2257132.1407453613050.202680826
2256910.83847688613093.0393179212256881.80425645613208.711264461
 2256727.3926183613209.242295101 2256686.6941874 613263.12660861
2256666.84746583613212.8482472452256485.35455635613298.523397401
2256457.81500003 613347.78200002 2256478.6803025613391.772610396
2256100.67527215613607.8828275352255908.81100002613812.760000005
2255668.58899999613837.503999993 2255552.3166585613776.045170755
2255399.41544656613828.288342148 2255393.7987657613945.048893735
2255485.00233443 614103.644610422255467.18011963614228.081788033
2255264.23404519614505.9912424922255108.30800004614563.614000008
2255081.72800002614604.6930000192254980.40000005614609.203000009
     2254537.073614450.4300000072254411.80699998614462.802000001
2253854.55500004 614350.939000012253745.45273623614387.735840291
2253592.64124814614287.2458329652253537.01500003614325.138000012

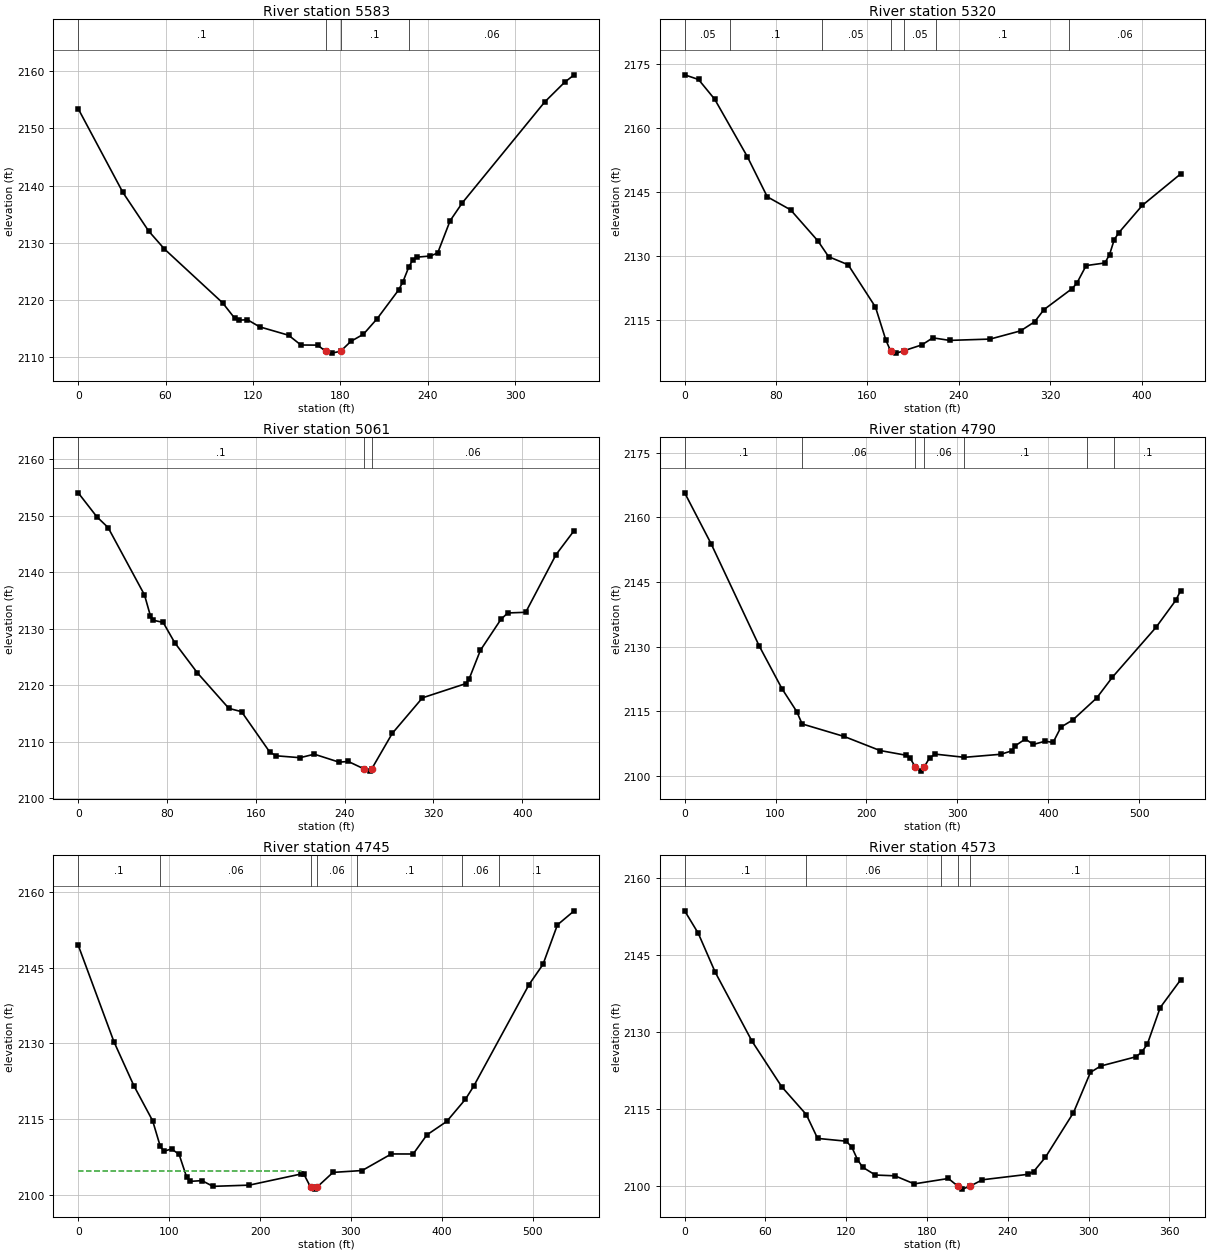
Type RM Length L Ch R = 1 ,5583    ,263.3,263.1,261.6
XS GIS Cut Line= 4
2257286.60837602612554.6871438042257386.21707295612655.812146428
2257430.42975001612688.3893264712257528.67612494612793.153424488
#Sta/Elev= 30
       0 2153.42    30.7 2138.78    48.4 2132.03    59.2  2128.9    99.1  2119.5
   107.5 2116.78   110.2 2116.46   116.2 2116.54   124.5  2115.3   144.4 2113.83
   152.9 2112.12   164.3  2112.1  169.892111.037   174.2  2110.7  180.172111.038
   187.2 2112.76   195.8    2114   205.3 2116.74   219.9 2121.72   222.8 2123.09
     227 2125.78   229.8 2127.03   232.6 2127.48   241.8 2127.68   246.8 2128.21
   255.3 2133.83   263.7 2136.97   320.3 2154.61   333.9 2158.04340.4867 2159.35
#Mann= 4 ,-1,0
       0      .1       0  169.89    .045       0  180.17      .1       0
  226.86     .06       0
Bank Sta=169.89,180.17
XS Rating Curve= 0 ,0
Exp/Cntr(USF)=0,0
Exp/Cntr=0.3,0.1

Type RM Length L Ch R = 1 ,5320    ,258.5,259.6,259.3
XS GIS Cut Line= 4
2257047.35231538612685.0444752662257164.91691181612777.561993456
2257284.86409981612843.4871654872257428.80240744612876.099395753
#Sta/Elev= 30
       0  2172.4    12.1 2171.31    26.3 2166.68    54.8 2153.27    72.3 2143.85
    92.7  2140.8   116.6 2133.53     126 2129.83   143.1 2127.94     167 2118.04
   176.1 2110.31  180.192107.812   185.3 2107.26   191.82107.808   207.7  2109.2
   217.2 2110.84   231.9 2110.24   267.4 2110.55     294 2112.47   306.3 2114.59
   314.5 2117.45   339.1 2122.36   343.2  2123.6   351.4 2127.75   367.8 2128.36
   371.9 2130.33     376 2133.83   380.1 2135.48   400.6 2141.85   434.1  2149.2
#Mann= 7 ,-1,0
       0     .05       0      40      .1       0     120     .05       0
  180.19    .045       0   191.8     .05       0   219.6      .1       0
  336.47     .06       0
Bank Sta=180.19,191.8
XS Rating Curve= 0 ,0
Exp/Cntr(USF)=0,0
Exp/Cntr=0.3,0.1

Type RM Length L Ch R = 1 ,5061    ,273.9,271.1,265.7
XS GIS Cut Line= 4
2256952.48395125612861.0656077492257126.46056146613022.950133794
2257164.53351115 613062.156401292257247.64547446613192.334397882
#Sta/Elev= 30
       0 2154.07    16.8 2149.82    26.9 2147.92    59.7 2135.98    65.1 2132.22
    67.8 2131.48    76.5 2131.11      87 2127.49   107.4 2122.15   135.7 2115.87
   147.1 2115.29   172.5 2108.14   178.2 2107.47   199.8 2107.13   212.7 2107.75
     235 2106.34   243.3 2106.46  257.412105.148   263.1 2104.75   264.42105.149
   282.9 2111.44   310.1 2117.74   349.3 2120.27   352.2 2121.12   362.3 2126.17
   380.8 2131.65   386.9 2132.78   403.1  2132.9   430.4 2143.11446.7412 2147.38
#Mann= 3 ,-1,0
       0      .1       0  257.41    .045       0   264.4     .06       0
Bank Sta=257.41,264.4
XS Rating Curve= 0 ,0
Exp/Cntr(USF)=0,0
Exp/Cntr=0.3,0.1

Type RM Length L Ch R = 1 ,4790    ,44.6,44.7,44.9
XS GIS Cut Line= 6
2256735.34618414612982.3184894662256769.87214223 613106.85553524
2256826.73260311 613106.855535242256988.98071437613116.050860642
2257012.77014232613114.9695230082257081.04315186613274.137259692
#Sta/Elev= 30
       0 2165.67      29  2153.9    81.8 2130.26     107 2120.28   123.3 2114.96
   129.2  2112.1   175.5 2109.19   214.8 2105.94   243.6 2104.84   247.6 2104.31
   253.9 2102.06   259.6 2101.16  263.262102.059   269.4 2104.21   275.7  2105.1
   307.7 2104.36   347.8 2105.07   359.8 2105.85   363.8 2107.05   374.8 2108.61
   383.5 2107.34   396.6  2108.1   405.3 2107.81     414 2111.37   427.1 2113.04
   453.2  2118.1   470.6 2122.94   518.5 2134.48   540.2 2140.73  545.61 2142.97
#Mann= 7 ,-1,0
       0      .1       0  129.23     .06       0   253.9    .045       0
  263.26     .06       0  306.88      .1       0  442.42     .06       0
  472.42      .1       0
Bank Sta=253.9,263.26
XS Rating Curve= 0 ,0
Exp/Cntr(USF)=0,0
Exp/Cntr=0.3,0.1

Type RM Length L Ch R = 1 ,4745    ,167.2,172.4,175.8
XS GIS Cut Line= 6
2256726.68557955613026.2366526622256761.21153764613150.773698436
2256818.07199852613150.7736984362256980.32010978613159.969023838
2257004.10953773613158.8876862032257072.38254727613318.055422888
#Sta/Elev= 30
       0 2149.44    39.3 2130.34    61.2 2121.65    81.9  2114.7    90.2 2109.68
    94.4 2108.68   102.7 2109.13     111 2108.05   119.3 2103.55   123.4 2102.72
   136.2 2102.86   148.2 2101.73   188.2 2101.97   245.1 2104.17   248.3 2104.13
  255.68 2101.55   260.3 2101.18   262.6 2101.55   280.3 2104.49   312.4 2104.86
   344.5 2108.14   368.5 2108.13   383.6 2111.91   405.4 2114.57     426 2118.96
   435.1 2121.55     496 2141.66   511.3 2145.63   527.2 2153.46  545.61 2156.24
#Mann= 7 ,-1,0
       0      .1       0      90     .06       0  255.68    .045       0
   262.6     .06       0  306.88      .1       0  422.42     .06       0
  462.42      .1       0
#XS Ineff= 2 , 0
          244.67 2104.73
Permanent Ineff=
       F       F
Bank Sta=255.68,262.6
XS Rating Curve= 0 ,0
Exp/Cntr(USF)=0,0
Exp/Cntr=0.3,0.1

Type RM Length L Ch R = 1 ,4573    ,244.6,251.4,247.2
XS GIS Cut Line= 2
2256702.35037753613023.6312055082256819.91440366613372.626301952
#Sta/Elev= 30
       0 2153.54    10.1 2149.16    22.7 2141.58      50 2128.17    72.1  2119.3
    90.3  2113.9    98.7 2109.26   119.8 2108.72     124 2107.63   128.3 2105.15
   132.1 2103.66   141.6 2102.13   156.1 2101.98   170.5 2100.41   195.8 2101.46
  202.922099.955   206.2 2099.39   211.82099.955   221.1 2101.21   254.9 2102.27
   259.1  2102.8   267.9  2105.6   288.7 2114.27   301.3 2122.11   308.9 2123.34
   335.1 2125.14   339.3 2126.03   343.5 2127.56   353.1 2134.71368.2647 2140.11
#Mann= 5 ,-1,0
       0      .1       0      90     .06       0     190      .1       0
  202.92    .045       0   211.8      .1       0
Bank Sta=202.92,211.8
XS Rating Curve= 0 ,0
Exp/Cntr(USF)=0,0
Exp/Cntr=0.3,0.1

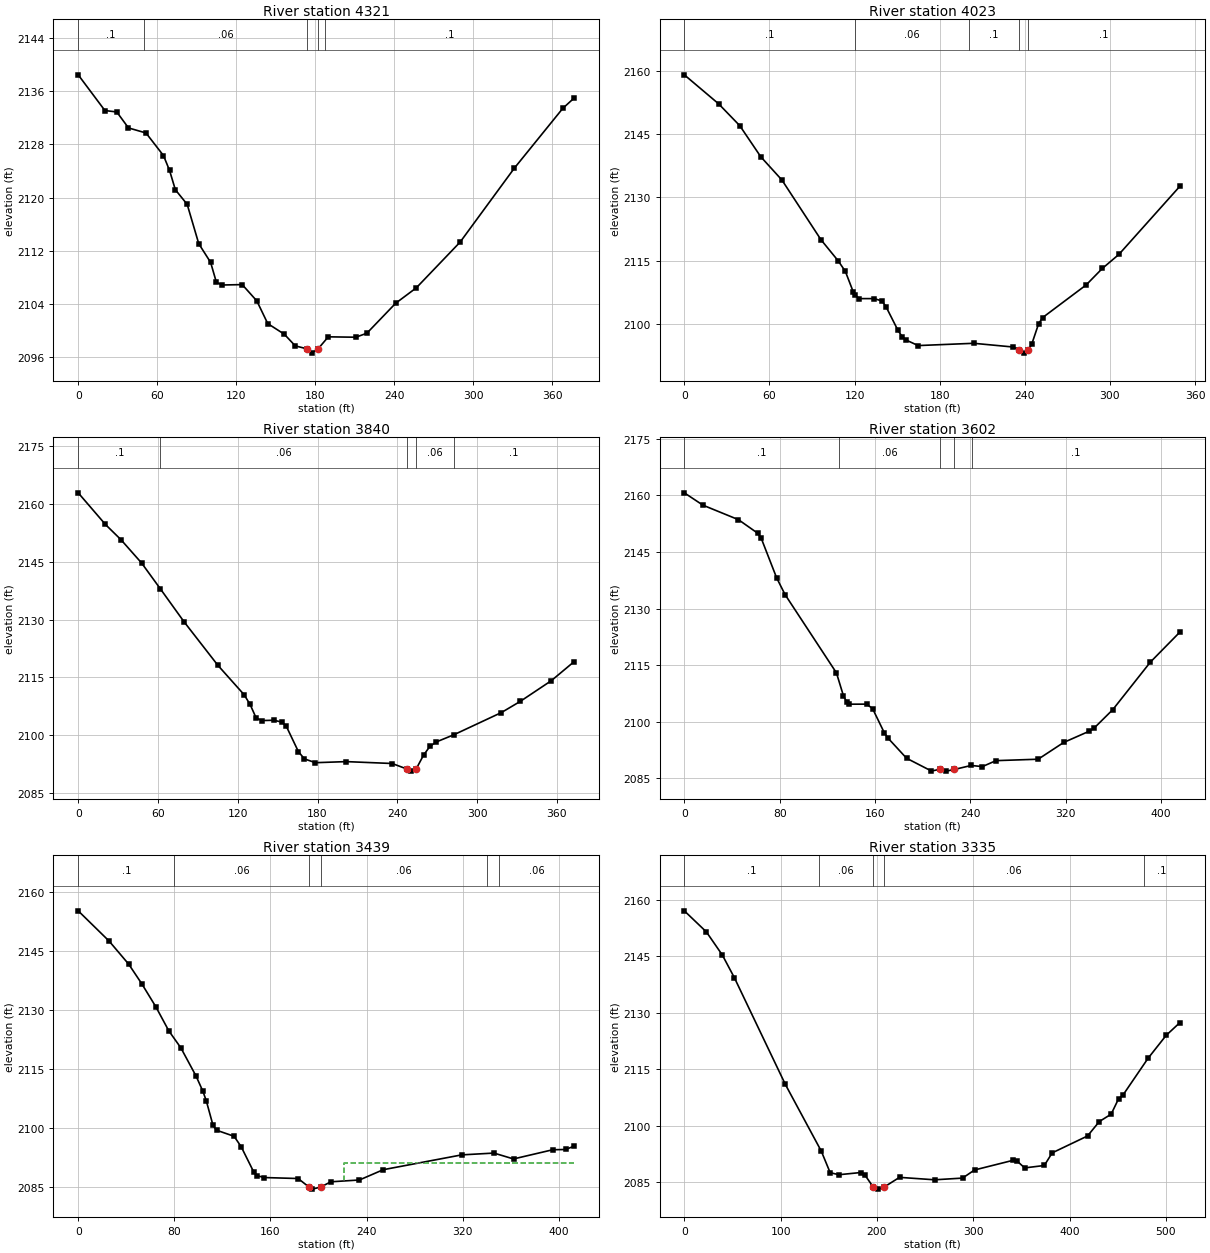
Type RM Length L Ch R = 1 ,4321    ,298.9,298.5,295.1
XS GIS Cut Line= 4
2256571.61686947 613066.924030362256627.93995713613181.562899993
2256653.61194932613267.0810220182256718.59259477613412.759424274
#Sta/Elev= 30
       0 2138.46    20.3 2133.09    29.3 2132.88    38.2 2130.48    51.5 2129.72
    64.8 2126.32    69.4 2124.09    73.8 2121.19    82.8 2118.99    91.6 2113.07
   100.6 2110.27     105 2107.26   109.5 2106.87   124.6 2106.93   135.7 2104.48
     144 2101.07   156.6 2099.47   164.9 2097.72  173.622097.285   177.4 2096.63
  182.282097.285     190 2099.08   210.9 2099.02   219.3 2099.62   241.2 2104.13
   256.9 2106.45   290.2 2113.33   331.3 2124.42   368.2 2133.43376.5299 2134.93
#Mann= 5 ,-1,0
       0      .1       0      50     .06       0  173.62    .045       0
  182.28     .06       0  187.73      .1       0
Bank Sta=173.62,182.28
XS Rating Curve= 0 ,0
Exp/Cntr(USF)=0,0
Exp/Cntr=0.3,0.1

Type RM Length L Ch R = 1 ,4023    ,181.7,183.2,182
XS GIS Cut Line= 4
2256325.05131194613209.6555911372256413.96962967613331.066898856
2256485.91047365613401.5244264642256554.26258203613471.953028384
#Sta/Elev= 30
       0 2159.04    24.2 2152.16    39.1 2146.98    53.9 2139.62    68.8 2134.11
    96.3 2119.97   108.5 2114.94   113.5 2112.46   119.2 2107.49   120.4 2106.87
   123.4 2106.01   133.9 2106.01   139.3 2105.44   142.1 2104.13   150.5 2098.54
   153.5    2097   156.4 2096.18   164.8 2094.88     204 2095.42     232 2094.53
  235.932093.844   239.3 2093.09  242.572093.842     245 2095.34   249.7 2100.04
   252.5  2101.5   283.2 2109.24   294.6 2113.15   306.3 2116.48349.3299 2132.65
#Mann= 5 ,-1,0
       0      .1       0     120     .06       0  200.49      .1       0
  235.93    .045       0  242.57      .1       0
Bank Sta=235.93,242.57
XS Rating Curve= 0 ,0
Exp/Cntr(USF)=0,0
Exp/Cntr=0.3,0.1

Type RM Length L Ch R = 1 ,3840    ,234.8,238,239.3
XS GIS Cut Line= 4
2256222.65371539613271.0948672662256303.38169461613422.300739316
2256372.11833046613494.6554514662256444.15995506613566.219190133
#Sta/Elev= 30
       0 2162.92    20.5  2154.7    32.2 2150.74    47.7 2144.69    61.8 2137.99
    79.5 2129.49   105.1 2118.12   124.8  2110.5   129.3 2107.97   133.9 2104.41
   138.4  2103.8   147.3 2103.88   153.4 2103.37   156.5 2102.33   165.6 2095.74
   170.1 2093.85   178.4 2092.86   201.6 2093.14   236.1 2092.65   247.4  2091.2
   250.4 2090.67  254.132091.201   259.7  2094.8   264.5 2097.09   269.2 2098.23
   282.6 2100.12   318.3 2105.88   332.4 2108.76   355.9 2114.17372.7509 2119.03
#Mann= 5 ,-1,0
       0      .1       0    61.8     .06       0   247.4    .045       0
  254.13     .06       0   282.6      .1       0
Bank Sta=247.4,254.13
XS Rating Curve= 0 ,0
Exp/Cntr(USF)=0,0
Exp/Cntr=0.3,0.1

Type RM Length L Ch R = 1 ,3602    ,164.7,162.6,159.2
XS GIS Cut Line= 4
2256055.54882122613396.0530896452256159.80133954613543.880399879
2256185.43890644613631.7806292542256319.33662103613682.748444898
#Sta/Elev= 30
       0  2160.7    15.6 2157.43    45.4 2153.58    61.5    2150    64.4 2148.74
    77.4 2138.18    84.5 2133.72   127.6 2112.96   133.5 2106.85   136.2 2105.27
   138.4 2104.66   153.1 2104.67     158 2103.43   167.7 2097.11   170.6 2095.75
   186.4 2090.33   207.2 2086.95   214.5 2087.37   219.7 2086.91  226.532087.354
   240.6 2088.41     250 2088.11   261.4 2089.69   296.8 2090.07   318.2 2094.51
   339.6 2097.49   343.9 2098.37   359.4 2103.22   390.9 2115.81415.7237 2123.79
#Mann= 5 ,-1,0
       0      .1       0     130     .06       0   214.5    .045       0
  226.53     .06       0  240.89      .1       0
Bank Sta=214.5,226.53
XS Rating Curve= 0 ,0
Exp/Cntr(USF)=0,0
Exp/Cntr=0.3,0.1

Type RM Length L Ch R = 1 ,3439    ,107.9,104.1,100.8
XS GIS Cut Line= 2
2255924.50537444613538.2510934842256203.25781376613842.143010091
#Sta/Elev= 30
       0 2155.12    25.7 2147.45      42 2141.59    52.8 2136.66    64.6 2130.77
    75.4 2124.66    85.4 2120.36    98.1 2113.17   103.8  2109.3   106.6 2106.88
   112.2 2100.65   115.1 2099.45   129.7 2097.91   135.6 2095.26   146.2 2088.76
   149.1  2087.9   154.7 2087.44     183 2087.19  192.02 2085.03   194.8  2084.5
  201.77 2085.03   210.2 2086.36     234 2086.82   253.8 2089.43   319.1 2093.19
   345.9 2093.65   362.2 2092.16   394.8 2094.49   405.6 2094.56412.3751 2095.38
#Mann= 6 ,-1,0
       0      .1       0      80     .06       0  192.02    .045       0
  201.77     .06       0     340      .1       0     350     .06       0
#XS Ineff= 2 , 0
                          220.98         2091.02
Permanent Ineff=
       F       F
Bank Sta=192.02,201.77
XS Rating Curve= 0 ,0
Exp/Cntr(USF)=0,0
Exp/Cntr=0.3,0.1

Type RM Length L Ch R = 1 ,3335    ,56.5,57.1,53.5
XS GIS Cut Line= 5
 2255883.9587432613567.0474874172255925.85554629613721.996827827
2256049.34163415613739.3516293642256098.06857693613757.373923268
2256133.12991857613931.222987906
#Sta/Elev= 30
       0 2157.08    22.9 2151.48    39.5 2145.32    51.9 2139.34   104.9 2110.94
   142.2 2093.21   151.4 2087.49   160.5 2086.95   183.1 2087.53   187.1    2087
  196.112083.682   200.8 2083.12  207.522083.683   223.4 2086.25   259.8  2085.6
   288.8 2086.05   301.3 2088.21     341 2090.76   345.1 2090.66   353.3 2088.76
   373.7  2089.4   381.9 2092.76   418.6 2097.25   430.8 2101.08   443.1 2103.04
   450.8 2107.13   455.3 2108.09   481.4 2117.89   500.2 2123.98514.5157 2127.39
#Mann= 5 ,-1,0
       0      .1       0     140     .06       0  196.11    .045       0
  207.52     .06       0  477.17      .1       0
Bank Sta=196.11,207.52
XS Rating Curve= 0 ,0
Exp/Cntr(USF)=0,0
Exp/Cntr=0.3,0.1

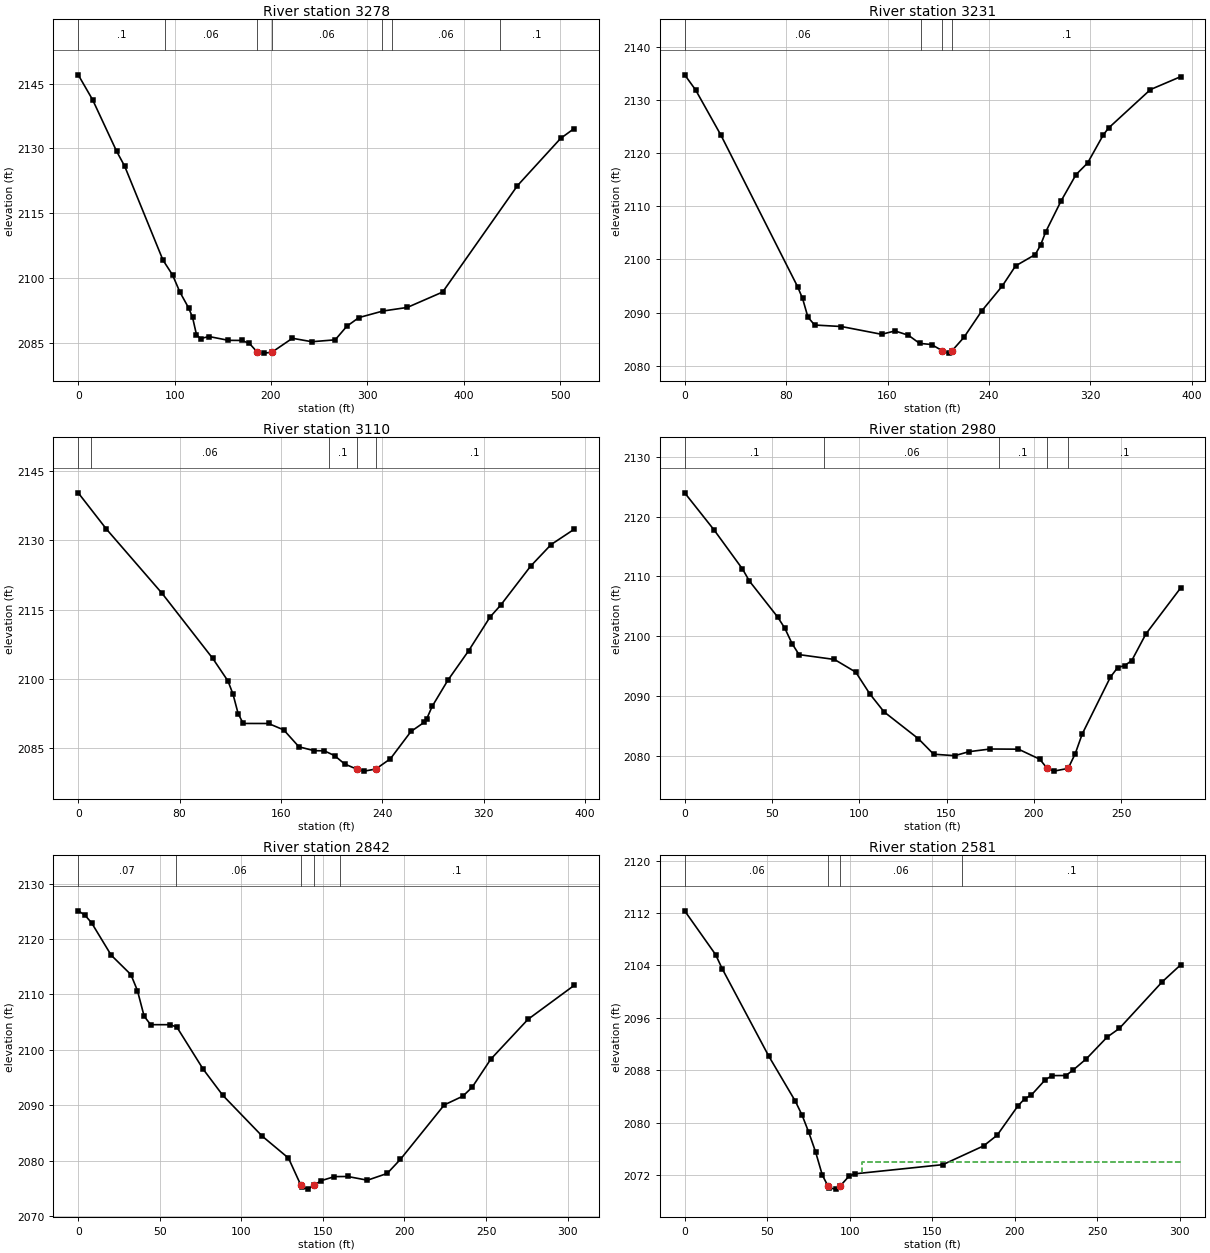
Type RM Length L Ch R = 1 ,3278    ,43.3,47,54.9
XS GIS Cut Line= 5
2255857.22536225613610.6947284012255899.12216533 613765.64406881
2256022.60825319613782.9988703472256071.33519597613801.021164251
2256106.39653761613974.870228889
#Sta/Elev= 30
       0 2147.03      15 2141.23    39.9  2129.3    48.2 2125.87    87.9 2104.14
    97.9 2100.67   105.5 2096.71   114.5 2093.07   118.6 2090.89   122.7 2086.84
   126.9 2085.93   135.6 2086.43   155.9 2085.54   169.7 2085.52   177.7 2084.81
   185.8 2082.79   185.8 2082.78   192.9 2082.58  200.91 2082.78   222.2 2086.02
   242.4 2085.22   266.6 2085.66   278.7 2088.81   291.2 2090.81   316.1 2092.33
   341.4 2093.16   378.1 2096.73   455.7 2121.37   500.5 2132.31514.5157 2134.59
#Mann= 7 ,-1,0
       0      .1       0      90     .06       0   185.8    .045       0
  200.91     .06       0  315.21      .1       0  325.21     .06       0
  437.17      .1       0
Bank Sta=185.8,200.91
XS Rating Curve= 0 ,0
Exp/Cntr(USF)=0,0
Exp/Cntr=0.3,0.1

Type RM Length L Ch R = 1 ,3231    ,117.6,120.8,127.7
XS GIS Cut Line= 4
 2255828.3471971 613632.634133472255838.18006889613728.649234422
2255955.01772185 613863.995822512255983.93793298613976.206241694
#Sta/Elev= 30
       0 2134.69     8.6 2131.86    28.7  2123.3      89 2094.91      93 2092.66
    97.2 2089.16   102.5 2087.67   123.6 2087.39   155.3 2085.93   165.9 2086.56
   176.5 2085.75   185.3 2084.22   194.7 2084.01   203.2 2082.84   208.2 2082.39
  210.95 2082.85   220.3 2085.36   234.4 2090.34   250.5    2095     261 2098.78
   276.5 2100.91   280.7 2102.67   284.8 2105.19   296.9 2110.99   308.7 2115.94
   317.8 2118.11   330.2  2123.4   334.4  2124.7   367.4 2131.92   391.2 2134.34
#Mann= 4 ,-1,0
       0     .06       0  186.52      .1       0   203.2    .045       0
  210.95      .1       0
Bank Sta=203.2,210.95
XS Rating Curve= 0 ,0
Exp/Cntr(USF)=0,0
Exp/Cntr=0.3,0.1

Type RM Length L Ch R = 1 ,3110    ,129.7,130,128.4
XS GIS Cut Line= 4
2255784.35766036613595.0191126572255788.10774584613772.886426544
2255793.87619839613851.9966329812255830.81780517 613980.97640753
#Sta/Elev= 30
       0 2140.31    22.2 2132.47    66.2 2118.52   106.2 2104.42   118.2 2099.53
   122.2 2096.65   126.2 2092.48   130.2 2090.34   150.2 2090.33   162.2 2088.94
   174.2 2085.28   186.2 2084.44   194.2 2084.41   202.3 2083.37   210.3 2081.55
  219.692080.461   225.7 2080.01  234.842080.461   246.4 2082.69   262.6  2088.6
     273 2090.58   275.1 2091.38   279.3 2094.02   291.7 2099.69   308.1 2106.08
     325 2113.39   333.4 2115.97   357.1 2124.44   373.2  2129.1391.3929 2132.41
#Mann= 5 ,-1,0
       0      .1       0      10     .06       0  197.91      .1       0
  219.69    .045       0  234.84      .1       0
Bank Sta=219.69,234.84
XS Rating Curve= 0 ,0
Exp/Cntr(USF)=0,0
Exp/Cntr=0.3,0.1

Type RM Length L Ch R = 1 ,2980    ,134.8,138.2,137.6
XS GIS Cut Line= 2
2255634.81571961613624.5505191432255681.37030717613904.790879595
#Sta/Elev= 30
       0 2123.98    16.9 2117.75    33.1 2111.25    37.1 2109.22    53.3  2103.2
    57.4 2101.32    61.5 2098.78    65.5 2096.93    85.8 2096.12      98    2094
   106.1 2090.34   114.2 2087.36   133.9 2082.86   142.6 2080.28   154.7 2080.03
   162.8  2080.7     175 2081.15   191.2 2081.12   203.4 2079.44  207.652077.909
   211.5 2077.45  219.65 2077.91   223.7 2080.35   227.7 2083.65   243.9 2093.19
     248 2094.75   252.1 2095.11   256.1 2095.94   264.2 2100.39 284.081 2108.07
#Mann= 5 ,-1,0
       0      .1       0      80     .06       0     180      .1       0
  207.65    .045       0  219.65      .1       0
Bank Sta=207.65,219.65
XS Rating Curve= 0 ,0
Exp/Cntr(USF)=0,0
Exp/Cntr=0.3,0.1

Type RM Length L Ch R = 1 ,2842    ,266.4,261,253.9
XS GIS Cut Line= 4
 2255534.5904465613637.0640631322255547.61830835613756.971633601
2255557.99429981 613836.921837822255631.25359184 613909.01834784
#Sta/Elev= 30
       0 2125.07     4.1  2124.3     8.2  2122.9    20.2 2117.07    32.3 2113.56
    36.3 2110.68    40.4 2106.06    44.4 2104.52    56.4 2104.52    60.5 2104.07
    76.6 2096.49    88.6 2091.78   112.8  2084.4   128.9 2080.44  136.442075.576
     137 2075.19     141 2074.84  144.682075.574   149.1 2076.38   157.1  2077.1
   165.2 2077.12   177.3 2076.45   189.4 2077.67   197.5 2080.21   224.4 2090.04
   235.8 2091.62   241.5 2093.23   252.9 2098.29   275.7 2105.48304.0193 2111.61
#Mann= 5 ,-1,0
       0     .07       0      60     .06       0  136.44    .045       0
  144.68     .06       0  160.61      .1       0
Bank Sta=136.44,144.68
XS Rating Curve= 0 ,0
Exp/Cntr(USF)=0,0
Exp/Cntr=0.3,0.1

Type RM Length L Ch R = 1 ,2581    ,140.7,137.5,131.8
XS GIS Cut Line= 4
2255297.50564188613928.9015502842255335.69303303613927.793394066
  2255472.487765613903.895519205 2255590.8608322613938.668093904
#Sta/Elev= 30
       0 2112.35    18.7 2105.67    22.7 2103.52    50.9 2090.16    67.1 2083.23
    71.2 2081.08    75.2 2078.48    79.3 2075.51    83.4 2071.95    86.82070.301
    87.4 2070.02    91.5 2069.82   94.222070.303    99.6 2071.81   103.1 2072.16
   156.4 2073.56   181.1 2076.43   189.3 2078.06   201.8 2082.51   205.9 2083.61
   210.1 2084.22   218.4 2086.52   222.6 2087.17   230.9 2087.18   235.1 2087.97
   243.4 2089.75     256 2093.07   263.3 2094.37   289.3  2101.5300.4447 2104.09
#Mann= 4 ,-1,0
       0     .06       0    86.8    .045       0   94.22     .06       0
   168.2      .1       0
#XS Ineff= 2 , 0
                          107.71         2073.98
Permanent Ineff=
       F       F
Bank Sta=86.8,94.22
XS Rating Curve= 0 ,0
Exp/Cntr(USF)=0,0
Exp/Cntr=0.3,0.1

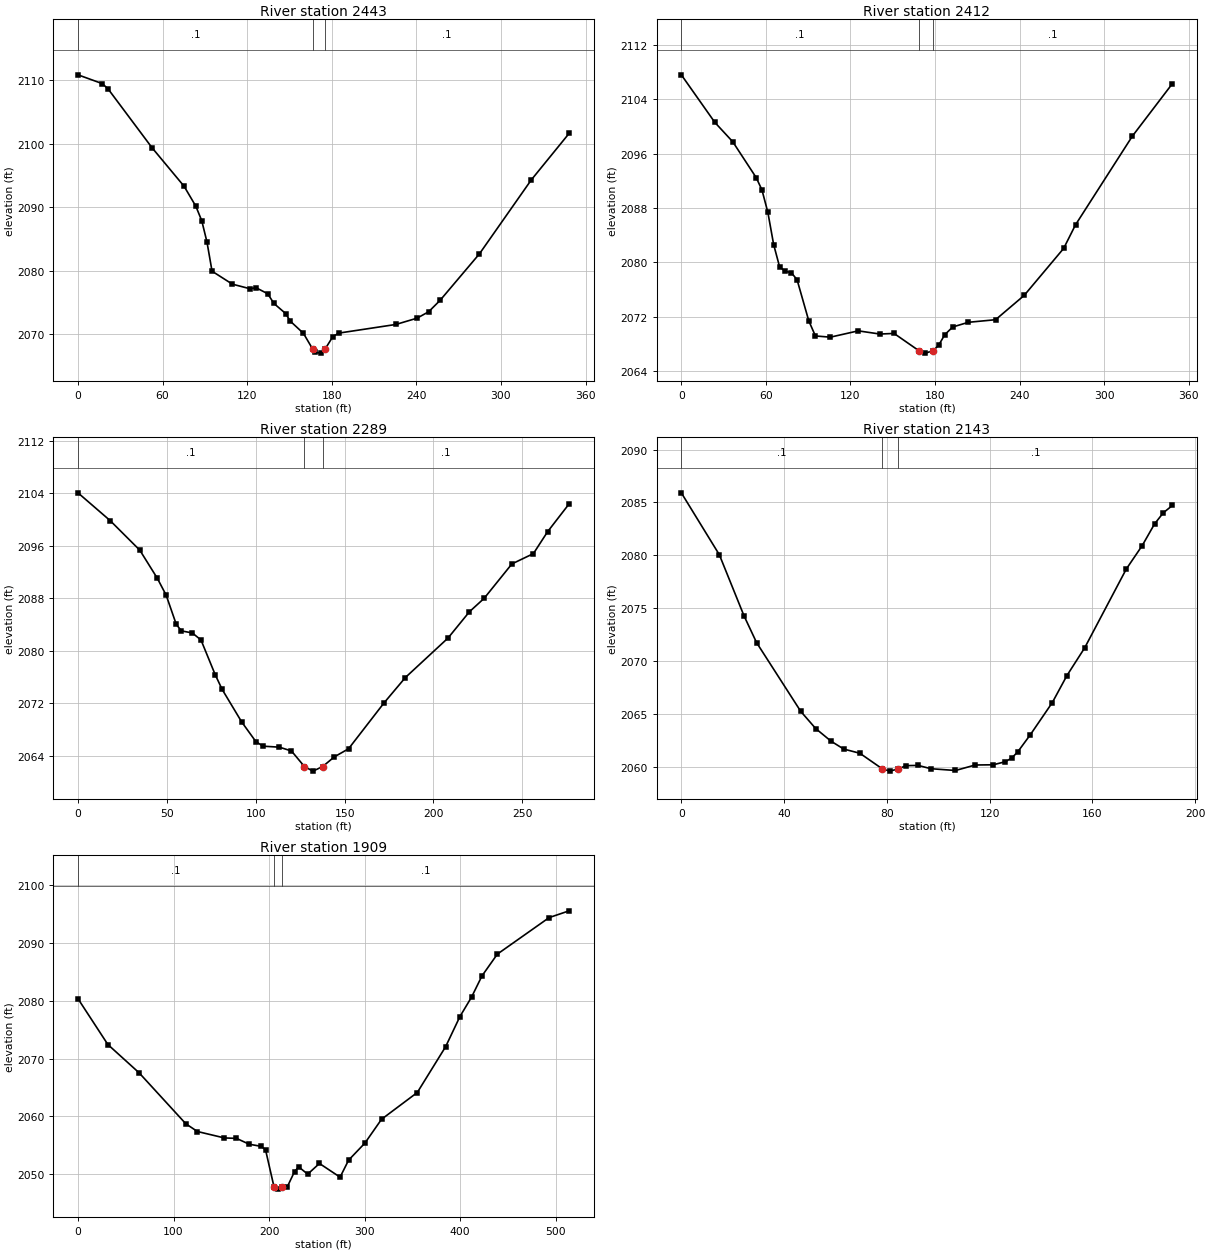
Type RM Length L Ch R = 1 ,2443    ,33.3,31.6,32.2
XS GIS Cut Line= 6
 2255331.5995289 614085.218264582255423.23626407614110.588012706
2255437.29365331614070.5785202392255450.81037374614026.784346052
2255458.37973718 614000.832242832255594.58686108613978.503584006
#Sta/Elev= 30
       0 2110.82    17.2 2109.44    21.3 2108.62    52.5 2099.36    75.3 2093.28
    83.6 2090.15    87.8 2087.87    91.5 2084.52    95.1 2079.93   109.5 2077.89
     122 2077.17   126.3 2077.33   134.6 2076.38     139 2074.85   147.3 2073.27
   150.5 2072.09   159.9 2070.16  166.512067.667   168.3 2067.14   172.4 2067.04
  175.242067.667   180.8 2069.64     185 2070.19   225.5 2071.55   240.5 2072.54
   248.7 2073.54   256.8 2075.33   284.8 2082.67   321.6 2094.31348.3822 2101.61
#Mann= 3 ,-1,0
       0      .1       0  166.51    .045       0  175.24      .1       0
Bank Sta=166.51,175.24
XS Rating Curve= 0 ,0
Exp/Cntr(USF)=0,0
Exp/Cntr=0.3,0.1

Type RM Length L Ch R = 1 ,2412    ,115.2,122.2,126.4
XS GIS Cut Line= 6
2255353.01522856614111.0601570832255444.65196373614136.429905209
2255458.70935298614096.420412742 2255472.2260734614052.626238555
2255479.79543684614026.6741353332255616.00256074614004.345476509
#Sta/Elev= 30
       0 2107.59    23.8 2100.58    36.5 2097.73    53.1 2092.46    57.2 2090.64
    61.4 2087.32    65.5 2082.59    69.7 2079.32    73.8 2078.65      78 2078.47
    82.1 2077.42    90.4 2071.37    95.1 2069.14   105.7 2068.96   125.5 2069.89
   140.9 2069.42   150.9 2069.51  168.422066.982   173.2 2066.61  178.792066.982
   182.6  2067.8   186.9 2069.33   192.5 2070.46   203.6 2071.15   222.9 2071.53
   243.2 2075.11   271.2 2082.03   279.6  2085.5   319.9 2098.55348.3822 2106.31
#Mann= 3 ,-1,0
       0      .1       0  168.42    .045       0  178.79      .1       0
Bank Sta=168.42,178.79
XS Rating Curve= 0 ,0
Exp/Cntr(USF)=0,0
Exp/Cntr=0.3,0.1

Type RM Length L Ch R = 1 ,2289    ,143.2,146.2,149.3
XS GIS Cut Line= 3
2255359.90875528614128.2533864532255429.04634199614177.717206027
2255620.29183652614181.964130162
#Sta/Elev= 30
       0 2104.06    18.1 2099.83    34.8 2095.32    44.6 2091.06    49.6 2088.48
    55.3 2084.02    58.2 2083.03    64.3 2082.72    69.2 2081.65    77.2 2076.36
    81.1 2074.12    92.1 2069.16   100.1 2066.16   104.1 2065.47   113.3 2065.32
   120.1 2064.74  127.392062.369   132.2 2061.67  137.662062.369   144.2 2063.84
   152.2 2065.07   172.2 2072.07   184.2 2075.93   208.2 2081.95   220.2 2085.94
   228.5 2087.99   244.1 2093.23   256.2  2094.8   264.2 2098.14276.3025 2102.38
#Mann= 3 ,-1,0
       0      .1       0  127.39    .045       0  137.66      .1       0
Bank Sta=127.39,137.66
XS Rating Curve= 0 ,0
Exp/Cntr(USF)=0,0
Exp/Cntr=0.3,0.1

Type RM Length L Ch R = 1 ,2143    ,234.7,234.5,233
XS GIS Cut Line= 2
2255331.97276609614244.7455807112255489.93688013614352.412663413
#Sta/Elev= 30
       0 2085.91    14.8 2080.05    24.4 2074.27    29.3 2071.73    46.5 2065.22
    52.3  2063.6    58.3  2062.4    63.2 2061.66    69.5 2061.26    78.2 2059.79
    81.1 2059.57   84.52 2059.78    87.4 2060.09    92.2 2060.11    97.1  2059.8
   106.7 2059.63   114.4 2060.15   121.4 2060.17   126.1 2060.46   128.6 2060.81
   130.9 2061.38   135.8    2063   144.4 2066.06   150.1 2068.62     157 2071.24
   173.2  2078.7   179.4 2080.92   184.2 2082.97   187.6 2084.02191.1671 2084.72
#Mann= 3 ,-1,0
       0      .1       0    78.2    .045       0   84.52      .1       0
Bank Sta=78.2,84.52
XS Rating Curve= 0 ,0
Exp/Cntr(USF)=0,0
Exp/Cntr=0.3,0.1

Type RM Length L Ch R = 1 ,1909    ,,,
XS GIS Cut Line= 4
2255202.33124141614306.4961562222255233.76274441614466.754883705
 2255388.7847375614531.5497725152255568.74932002614500.368241197
#Sta/Elev= 30
       0 2080.35    31.3 2072.42    63.9 2067.54   112.8 2058.72     125 2057.37
   153.2 2056.26   165.9 2056.18   179.2 2055.17   191.9  2054.8   196.3  2054.2
  205.15  2047.8   209.3  2047.4   213.6 2047.81     219 2047.78   226.6 2050.42
     231 2051.25   240.4 2049.99   252.7 2051.84   274.3 2049.47   283.2 2052.41
   300.3 2055.37   317.7 2059.49   355.1 2064.12   384.8 2072.06   399.7 2077.26
   411.9 2080.63   422.8  2084.3   438.9 2088.07   493.1 2094.39     514 2095.56
#Mann= 3 ,-1,0
       0      .1       0  205.15    .045       0   213.6      .1       0
Bank Sta=205.15,213.6
XS Rating Curve= 0 ,0
Exp/Cntr(USF)=0,0
Exp/Cntr=0.3,0.1
LCMann Table=0

Chan Stop Cuts=-1
Use User Specified Reach Order=0
Composite Channel Slope=5